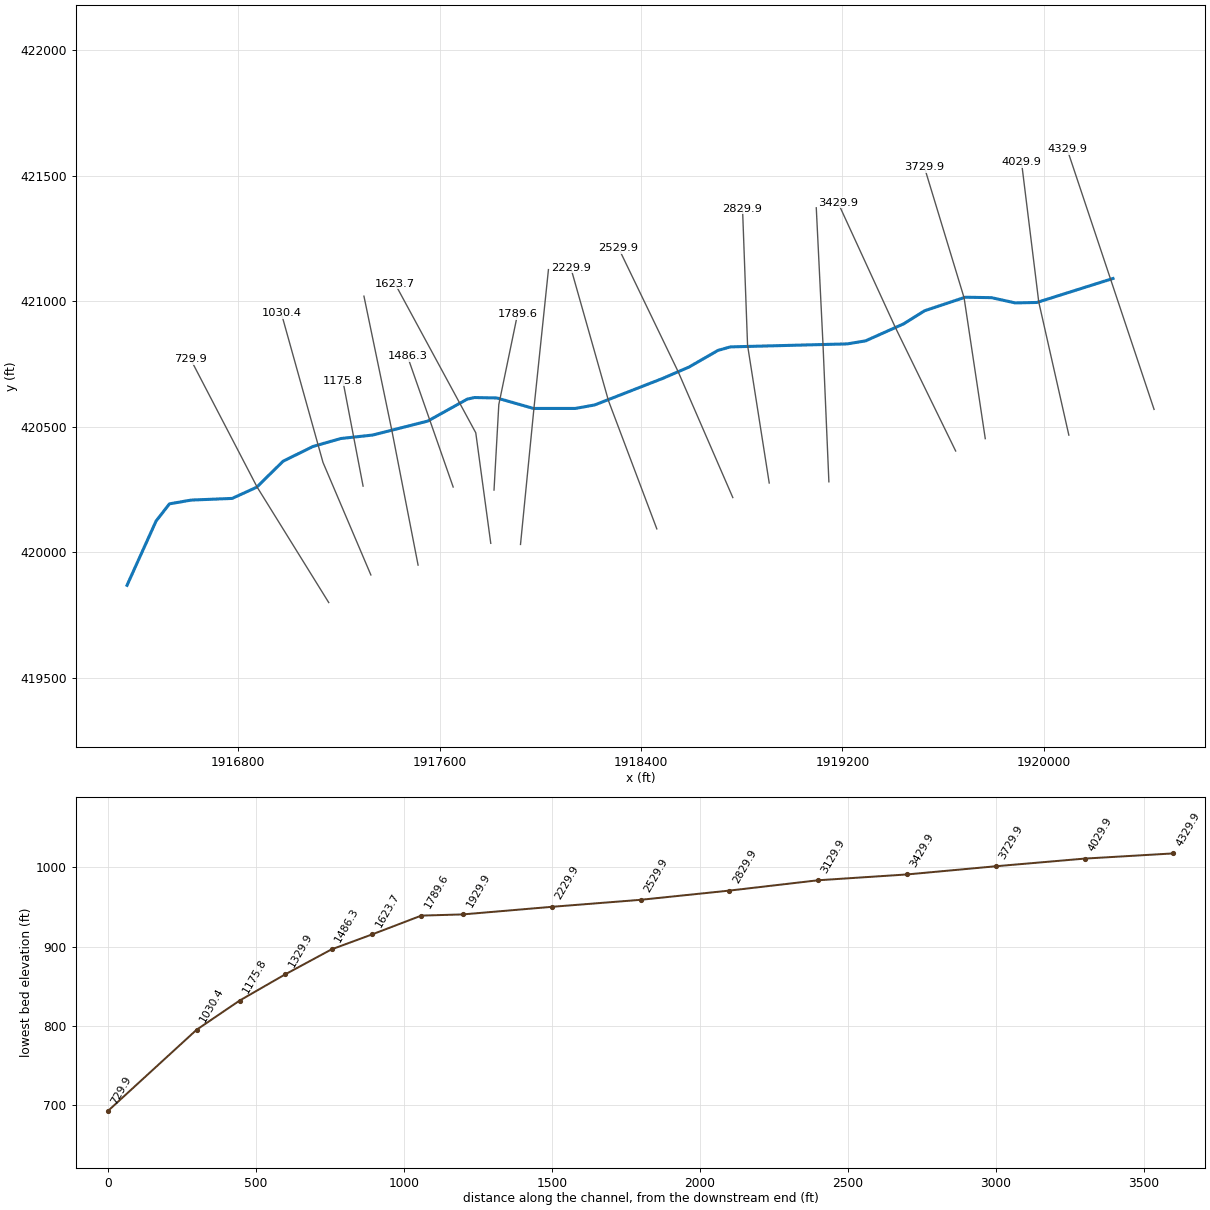
--- CaneBranch.prj (project) ---

Proj Title=CaneBranch
Current Plan=p01
Default Exp/Contr=0,0
English Units
Geom File=g01
Flow File=f01
Plan File=p01
BEGIN DESCRIPTION:
END DESCRIPTION:
DSS Export Rating Curves= 0
DSS Export Rating Curve Sorted= 0
DSS Export Volume Flow Curves= 0
DXF OffsetX= 0
DXF OffsetY= 0
DXF ScaleX= 0
DXF ScaleY= 0

--- CaneBranch.p01 (plan) ---

Plan Title=Floodplain
Program Version=4.00
Geom File=g01
Flow File=f01
K Sum by GR=0
Std Step Tol=0.01
Critical Tol=0.01
Num of Std Step Trials=20
Max Error Tol=0.3
Flow Tol Ratio=0.001
Split Flow NTrial=30
Split Flow Tol=0.02
Split Flow Ratio=0.02
Log Output Level=0
Friction Slope Method=1
Unsteady Friction Slope Method=2
Unsteady Bridges Friction Slope Method=1
Global Log Level=0
CheckData=False
Run HTab=0
Run UNet=0
Run PostProcess=0
UNET Theta=0
UNET Theta Warmup=0
UNET ZTol=0
UNET ZSATol=0
UNET MxIter=0
UNET MaxInSteps=0
UNET DtIC=0
UNET DtMin=0
UNET MaxCRTS=0
UNET WFStab=0
UNET SFStab=0
UNET WFX=0
UNET SFX=0
UNET DSS MLevel=0
UNET DZMax Abort=0
UNET Convert EG Bridges=0
UNET Use Existing IB Tables=0
UNET Froude Limit=0
UNET Froude Power=0
Write IC File=0
Echo Input=False
Echo Output=False
Write Detailed=0

--- CaneBranch.f01 (steady flow) ---

Flow Title=NFF Regression Equation
Program Version=4.10
Number of Profiles= 1
Profile Names=P100yr
River Rch & RM=CaneBranch,Main            ,4329.9
 520.641
River Rch & RM=CaneBranch,Main            ,3129.9
544.4797
River Rch & RM=CaneBranch,Main            ,729.9
  593.11
Boundary for River Rch & Prof#=CaneBranch,Main            , 1
Up Type= 0
Dn Type= 3
Dn Slope=0.269524
DSS Import GetInterval= 0
DSS Import GetPeak= 0
DSS Import FillOption= 0

--- CaneBranch.g01 (geometry) ---

Geom Title=USGS 3m DEM
Program Version=4.10

River Reach=CaneBranch      ,Main
Reach XY= 30
     1920275.309      421090.333     1919973.025      420994.847
      1919886.42      420993.111      1919792.67      421013.944
     1919688.503      421015.681     1919527.045      420961.861
     1919443.712      420909.778      1919292.67      420842.069
     1919219.753      420829.917     1918755.301      420817.984
     1918705.865      420803.875     1918591.281      420737.903
     1918487.115      420692.764     1918216.281      420586.861
     1918139.892      420572.972     1917973.226      420572.972
     1917827.392      420614.639     1917738.851      420616.375
     1917709.915      420609.945     1917553.087      420522.625
     1917334.337       420467.07     1917207.601       420453.18
     1917098.226      420421.931     1916978.434      420362.903
     1916873.577      420259.355     1916776.167       420214.82
      1916613.07      420208.134     1916527.082      420193.225
     1916473.815      420124.503     1916358.474      419868.926

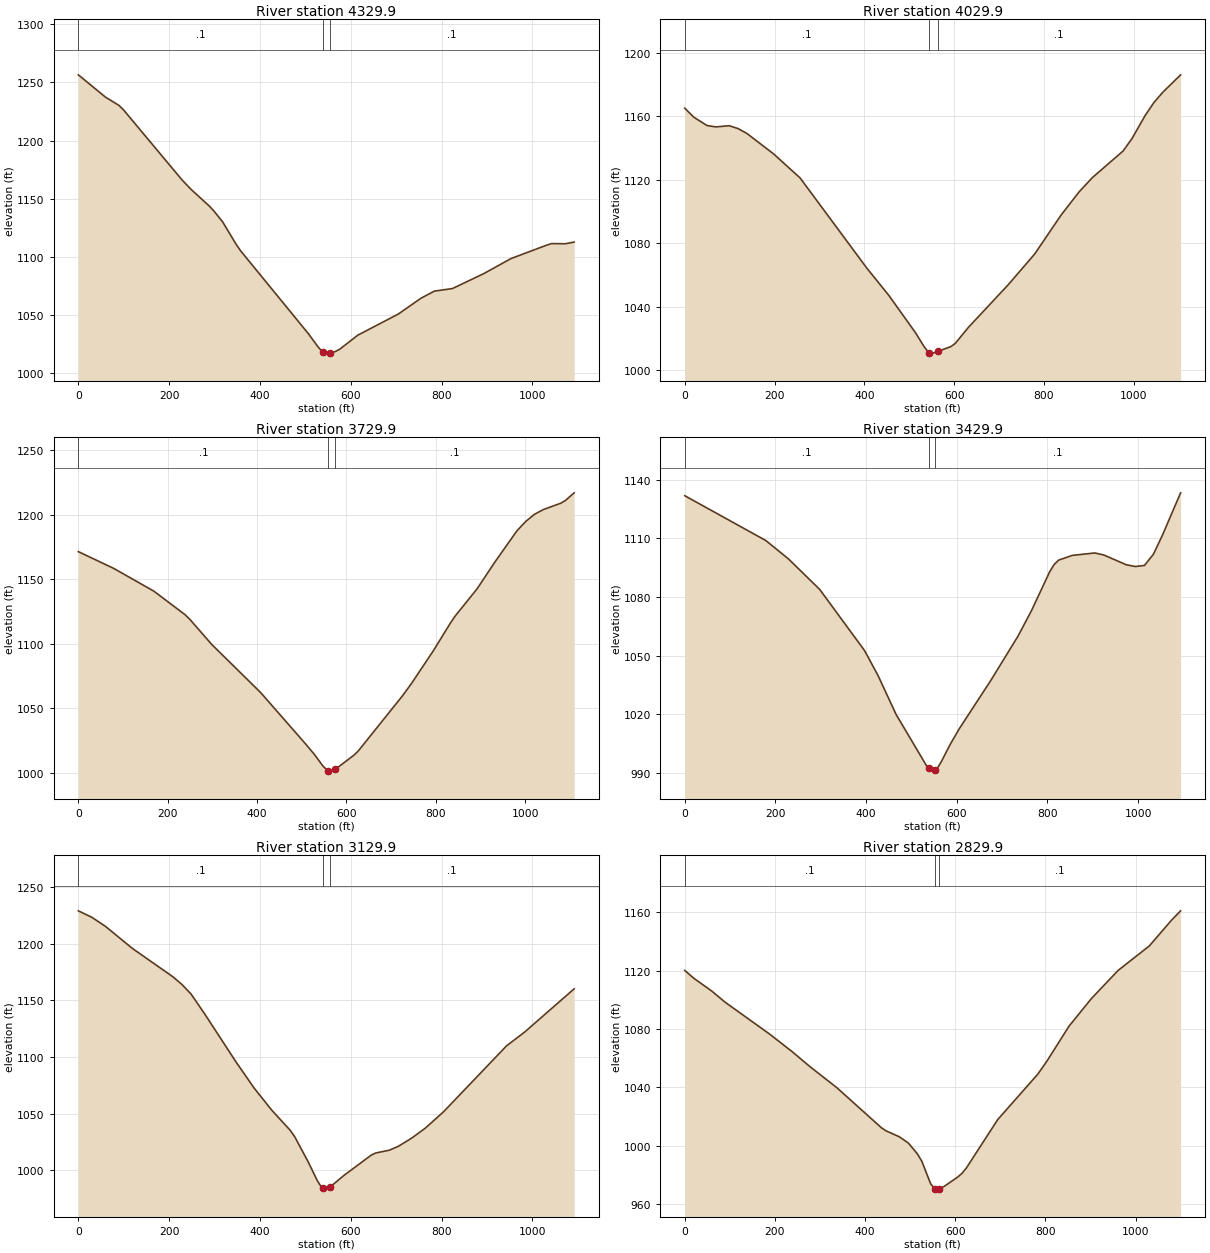
Type RM Length L Ch R = 1 ,4329.9  ,302.3,300,295.5
XS GIS Cut Line= 3
     1920438.483       420569.19     1920265.822      421087.171
     1920093.161      421605.152
#Sta/Elev= 30
       0 1256.54    59.6 1237.42    89.4 1230.27    99.3 1226.52   228.3 1166.22
   248.2 1158.07   287.9 1143.92   297.8 1139.82   317.7 1130.17   347.4 1110.94
   357.4 1105.22   506.3 1034.14   526.2 1023.55   536.1 1018.86   538.5 1018.47
     546 1017.25   553.5 1017.43   565.8 1018.58   575.8 1020.64   615.5 1032.68
   704.8 1050.86   754.5 1064.43   784.2 1070.56     824 1072.78   893.4  1085.7
     953 1098.58  1032.4 1110.22  1042.4 1111.44  1072.2 1111.28    1092 1112.73
#Mann= 3 , 0 , 0
       0      .1       0   538.5    .045       0   553.5      .1       0
Bank Sta=538.5,553.5
XS Rating Curve= 0 ,0
Exp/Cntr=0.3,0.1

Type RM Length L Ch R = 1 ,4029.9  ,301.7,300,303.9
XS GIS Cut Line= 3
     1920099.935      420466.768     1919980.423      420996.715
     1919911.861      421553.789
#Sta/Elev= 30
       0 1164.98    19.8 1159.37    49.4 1154.07    69.1 1153.19    98.8 1153.94
   118.5 1152.16   138.3 1149.08   197.6 1136.23   256.8 1121.06     405 1064.44
   454.4 1047.11   513.6 1023.69   533.4 1014.67   543.3 1011.04   553.1 1010.71
     563 1011.75   592.5 1014.79   602.3 1016.77   631.9 1026.97   720.5 1053.79
   779.6 1073.21   838.7 1097.85     878 1112.14   907.6 1121.18   976.5 1138.04
   996.2 1145.87  1025.8 1160.53  1045.4 1168.65  1065.2 1175.13  1104.5 1185.99
#Mann= 3 , 0 , 0
       0      .1       0   543.3    .045       0     563      .1       0
Bank Sta=543.3,563
XS Rating Curve= 0 ,0
Exp/Cntr=0.3,0.1

Type RM Length L Ch R = 1 ,3729.9  ,293,300,303.1
XS GIS Cut Line= 3
     1919767.927      420452.702     1919683.762      421013.619
      1919526.31       421532.67
#Sta/Elev= 30
       0 1171.36    79.6 1158.28   169.2 1140.66   238.8 1122.45   248.8 1119.12
   298.5 1099.38     408 1062.03   507.5  1022.6   527.4 1014.42   547.3 1005.09
   557.2 1001.68   559.7 1001.53   567.2 1001.07   574.7 1002.34   616.5 1013.39
   626.4 1016.68     725  1059.3   744.7 1068.65     794 1094.21   833.5 1116.41
   843.3 1121.35   892.6 1142.63   932.1 1163.22   981.4 1187.46  1001.1 1194.74
  1020.8 1200.32  1040.6    1204    1080 1208.97  1089.9 1211.02  1109.6 1216.99
#Mann= 3 , 0 , 0
       0      .1       0   559.7    .045       0   574.7      .1       0
Bank Sta=559.7,574.7
XS Rating Curve= 0 ,0
Exp/Cntr=0.3,0.1

Type RM Length L Ch R = 1 ,3429.9  ,309.3,300,291.4
XS GIS Cut Line= 3
     1919650.326      420403.535     1919411.371      420894.022
     1919182.821      421392.399
#Sta/Elev= 30
       0 1131.91   178.6 1108.97   228.2 1099.64   297.6 1083.91   396.8 1052.48
   426.6 1039.62   466.2 1019.81   535.7  992.59   538.1  992.15   545.6  990.76
   553.1   991.4   555.6  991.62   565.5  995.42   585.5 1004.45   605.4 1012.42
   675.2 1037.27     735 1059.88   764.9 1073.03   804.8 1092.83   814.8 1096.66
   824.7 1098.89   854.6 1101.32   904.5 1102.58   924.4 1101.54   974.2 1096.52
   994.2 1095.63  1014.1 1096.18  1034.1    1102    1054  1111.8  1093.9  1133.4
#Mann= 3 , 0 , 0
       0      .1       0   538.1    .045       0   553.1      .1       0
Bank Sta=538.1,553.1
XS Rating Curve= 0 ,0
Exp/Cntr=0.3,0.1

Type RM Length L Ch R = 1 ,3129.9  ,297.5,300,299.7
XS GIS Cut Line= 3
     1919146.699      420280.896     1919123.359      420826.402
     1919096.586      421371.746
#Sta/Elev= 30
       0 1228.97    29.8 1223.25    59.6 1215.32   119.1 1195.79   208.5 1170.73
   228.3 1163.95   248.2  1155.6     278 1138.19   347.5 1095.52   387.2  1072.6
   426.9 1052.67   466.6 1035.38   476.5 1029.72   506.3 1007.43   526.2  991.03
   536.1   984.7   538.5  984.39     546  983.44   553.5  984.98   585.7  995.76
   645.3  1013.5   655.2 1015.35     685 1017.79   704.8 1021.21   734.6 1028.55
   764.4 1037.31   804.1 1051.58   943.1 1109.84   982.8 1121.94    1092 1160.17
#Mann= 3 , 0 , 0
       0      .1       0   538.5    .045       0   553.5      .1       0
Bank Sta=538.5,553.5
XS Rating Curve= 0 ,0
Exp/Cntr=0.3,0.1

Type RM Length L Ch R = 1 ,2829.9  ,294.3,300,309.3
XS GIS Cut Line= 3
     1918909.657      420276.114     1918823.607      420824.837
     1918803.634      421368.734
#Sta/Elev= 30
       0 1120.09    19.8 1114.79    59.5 1106.05    89.3 1098.38   188.4 1076.47
     238 1064.53   277.7 1054.23   337.2 1039.86   436.4 1012.34   446.3 1010.33
   476.1  1006.2   495.9 1001.95   515.8  994.58   525.7   989.5   545.5  973.95
   555.4  970.42   562.9  970.46   575.2  972.27   604.9   978.6   614.8  981.21
   624.7  984.97     694    1018     783 1049.13   802.8 1057.84   852.3 1081.99
   901.8 1100.83   961.2 1120.13  1030.4  1136.9  1079.9 1154.63  1099.7 1160.89
#Mann= 3 , 0 , 0
       0      .1       0   555.4    .045       0   562.9      .1       0
Bank Sta=555.4,562.9
XS Rating Curve= 0 ,0
Exp/Cntr=0.3,0.1

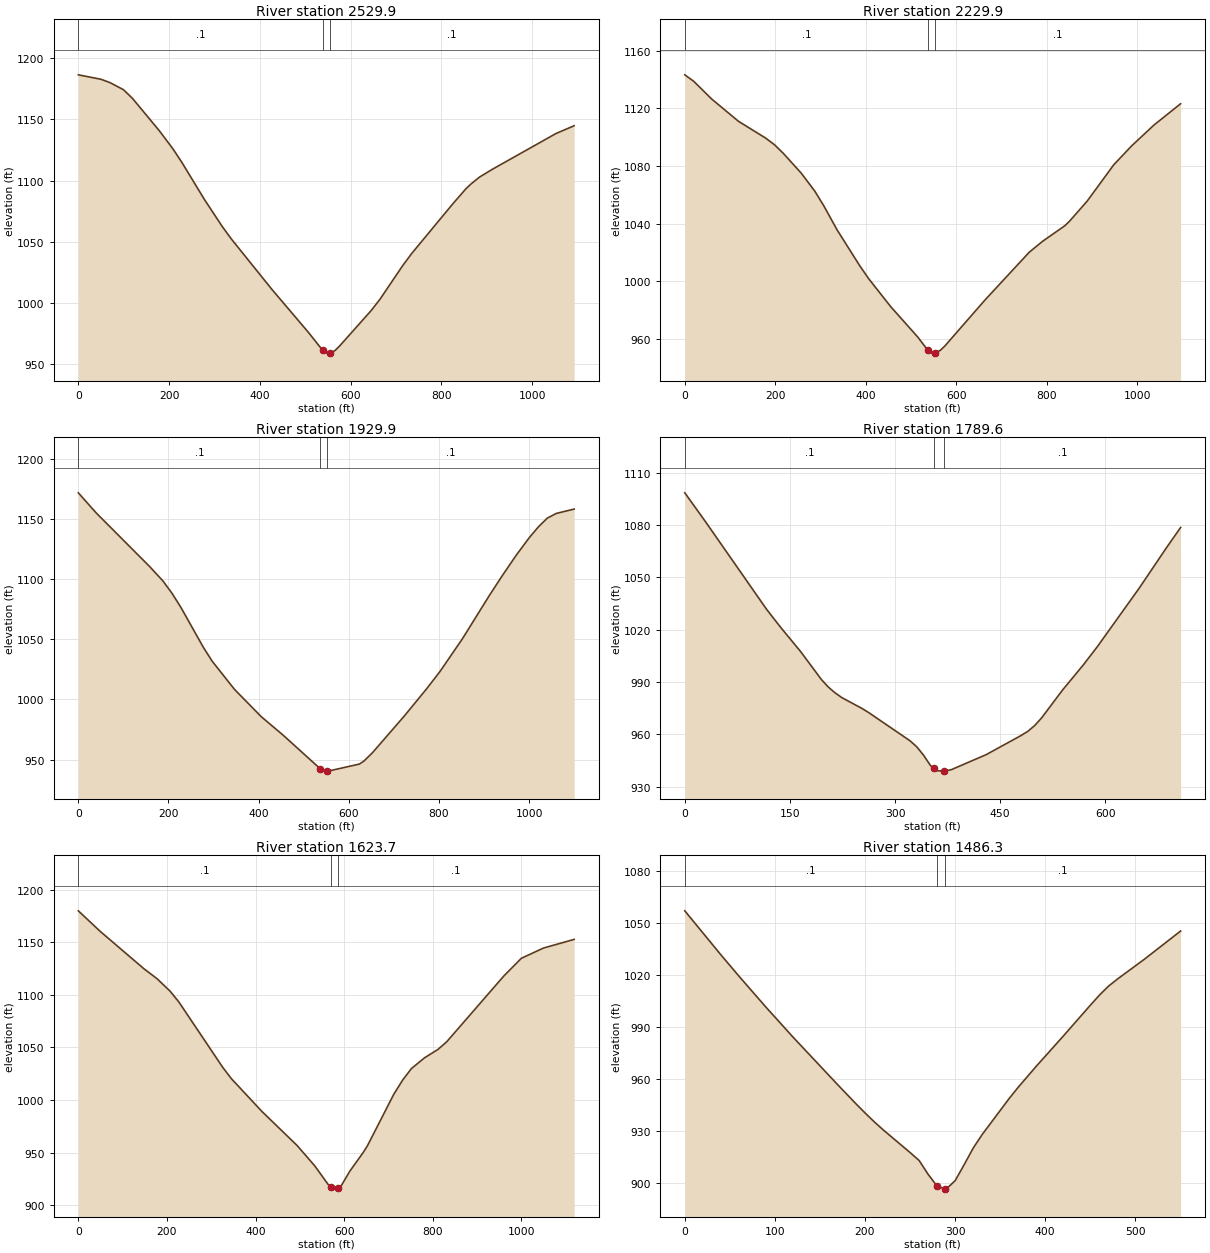
Type RM Length L Ch R = 1 ,2529.9  ,301.1,300,296.1
XS GIS Cut Line= 3
     1918765.027      420218.234      1918547.97      420719.135
      1918310.97      421211.594
#Sta/Elev= 30
       0 1186.47    49.6 1182.86    69.5 1180.14    99.3 1174.35   119.1 1167.29
   178.7 1140.62   208.4 1125.92   228.3 1114.74   277.9 1084.44   317.6 1062.11
   337.5 1052.01   426.8  1010.8   506.2  976.11   538.4  961.09   545.9  958.85
   553.4  958.82   555.8  958.81   565.8  961.03   575.7  964.68   645.3  993.68
   665.2  1003.2   714.8 1030.48   734.7 1040.41   824.1 1080.51     854 1093.28
   863.9 1096.78   883.8  1102.8   913.6  1109.5  1052.7 1138.52  1092.4 1144.83
#Mann= 3 , 0 , 0
       0      .1       0   538.4    .045       0   553.4      .1       0
Bank Sta=538.4,553.4
XS Rating Curve= 0 ,0
Exp/Cntr=0.3,0.1

Type RM Length L Ch R = 1 ,2229.9  ,310.3,300,291.4
XS GIS Cut Line= 3
     1918463.109      420093.577     1918271.188      420603.499
     1918121.046      421134.029
#Sta/Elev= 30
       0 1143.37    19.8 1138.87    59.4 1126.57   118.9 1111.02   178.3 1099.51
   198.1 1094.85   217.9 1088.79   257.6 1074.98   287.3  1062.6   307.1 1052.48
   336.8 1035.59   386.3 1010.96   406.2 1001.85   455.7   982.1   515.1  961.15
   537.3  951.97   544.8  949.98   552.3  950.04   564.5  951.82   574.4  954.73
     663  986.66   761.4 1020.06     791 1027.68   840.2  1038.5   850.1 1041.48
   889.4 1055.54   948.5  1080.9   987.9    1094  1037.1 1108.43  1096.2 1123.28
#Mann= 3 , 0 , 0
       0      .1       0   537.3    .045       0   552.3      .1       0
Bank Sta=537.3,552.3
XS Rating Curve= 0 ,0
Exp/Cntr=0.3,0.1

Type RM Length L Ch R = 1 ,1929.9  ,142.6,140.3,138.1
XS GIS Cut Line= 3
     1917921.615      420031.507     1917974.942      420572.936
      1918032.62      421125.661
#Sta/Elev= 30
       0 1171.72    39.6 1155.03   158.3 1110.41   187.9 1098.39   207.7 1088.28
   227.5 1076.53     277 1043.53   296.8 1031.85   346.2 1008.47   405.6  985.76
     455  970.09   536.5  942.44     544  940.86   551.5  940.55     554  940.45
   623.4  946.31   633.4  948.78   653.2  956.08   722.7   986.1   772.3 1008.74
   802.1  1023.2   851.7 1050.28   911.2  1086.1     941 1103.22   970.8  1119.6
  1000.5 1134.59  1020.4 1143.39  1040.2 1150.69  1060.1 1154.59  1099.8 1158.21
#Mann= 3 , 0 , 0
       0      .1       0   536.5    .045       0   551.5      .1       0
Bank Sta=536.5,551.5
XS Rating Curve= 0 ,0
Exp/Cntr=0.3,0.1

Type RM Length L Ch R = 1 ,1789.6  ,150.2,165.9,181.7
XS GIS Cut Line= 3
     1917816.428      420248.135     1917835.422      420588.302
     1917909.672      420947.464
#Sta/Elev= 30
       0 1098.54    29.2 1082.18   116.8 1031.68   136.3 1021.62   165.5 1007.38
   194.7  991.57   204.4  987.29   214.2   983.9   223.9  981.14   253.1  974.82
   262.8  972.39   321.2  956.39     331  952.87   340.7  948.05   350.6   942.1
   355.3   940.7   360.5  939.16   370.3  938.94   380.4  939.79   429.9  948.38
   479.5  959.31   489.4  961.76   499.3  965.11   509.2  969.54   538.9  985.42
   568.7  999.92   588.5 1010.26     648 1043.69   687.6 1067.29   707.4 1078.66
#Mann= 3 , 0 , 0
       0      .1       0   355.3    .045       0   370.3      .1       0
Bank Sta=355.3,370.3
XS Rating Curve= 0 ,0
Exp/Cntr=0.3,0.1

Type RM Length L Ch R = 1 ,1623.7  ,140.9,137.3,133.7
XS GIS Cut Line= 3
     1917803.472      420036.014     1917743.905      420476.064
     1917423.012       421069.75
#Sta/Elev= 30
       0 1179.94    49.3 1160.43     148 1124.88   177.6 1115.41   207.2  1103.5
     227 1093.19   325.6 1031.26   345.4 1020.33   414.5  989.08   493.7  956.79
   533.4  937.49   563.2  920.07   570.1  917.11   573.1  915.82     583  915.31
   585.1  915.94   592.9  918.29   612.8  932.45   642.6  949.99   652.5  956.62
     712 1005.59   731.9 1019.01   751.7 1029.97   781.5 1040.24   811.3 1048.07
   831.1 1055.32   960.1 1117.92   999.8 1134.82  1049.4  1144.5  1118.9 1152.79
#Mann= 3 , 0 , 0
       0      .1       0   570.1    .045       0   585.1      .1       0
Bank Sta=570.1,585.1
XS Rating Curve= 0 ,0
Exp/Cntr=0.3,0.1

Type RM Length L Ch R = 1 ,1486.3  ,159.7,156.4,153.5
XS GIS Cut Line= 2
     1917654.115      420260.222     1917472.807       420779.97
#Sta/Elev= 30
       0 1057.16      40  1031.8      60 1019.51    90.1 1001.54   120.1  984.26
   170.1  956.56   190.2  945.64   200.2  940.39   210.2  935.39   220.2   930.7
   250.2  917.54   260.2  912.96   270.2  904.96   280.2  898.13   289.1  896.63
   290.2  896.44   300.2  901.36   310.3  910.69   320.3  920.21   330.3  928.06
   360.3  948.89   370.3  955.34   390.3  967.44   420.4  984.93   450.4 1002.73
   460.4 1008.49   470.4 1013.64   480.4 1017.77   510.4 1029.26   550.5  1045.5
#Mann= 3 , 0 , 0
       0      .1       0   280.2    .045       0   289.1      .1       0
Bank Sta=280.2,289.1
XS Rating Curve= 0 ,0
Exp/Cntr=0.3,0.1

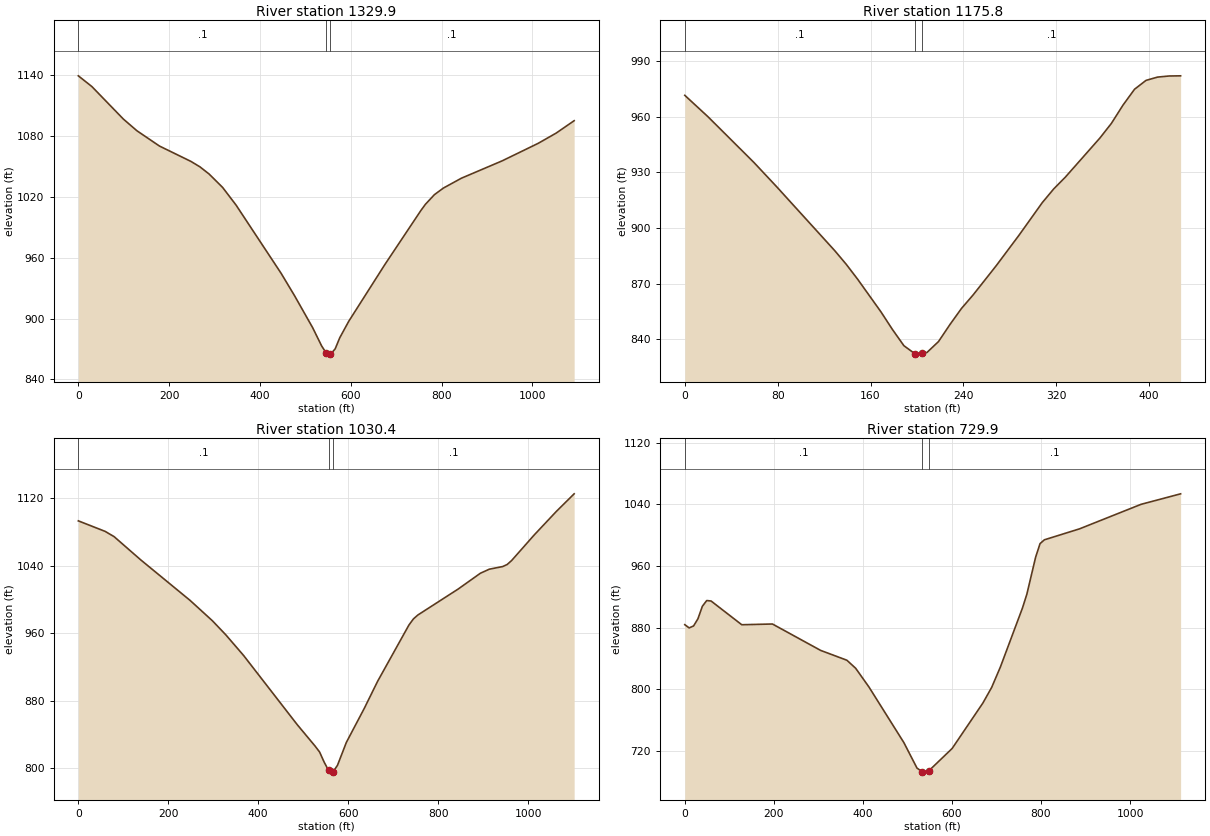
Type RM Length L Ch R = 1 ,1329.9  ,154.1,154.1,153.7
XS GIS Cut Line= 3
     1917514.753      419949.311     1917410.527       420485.26
      1917299.66      421019.957
#Sta/Elev= 30
       0 1139.45    29.8 1128.88    99.3 1096.76     129  1085.3   178.7  1070.2
   248.2 1055.01     268 1049.64   287.9 1042.67   317.7 1029.44   347.4    1012
   446.7  944.66   476.5  922.43   516.2  891.01   536.1  872.91     546  866.15
   553.5  865.28   555.9     865   565.8  870.26   575.8  881.12   595.6  897.37
   675.1  953.29   754.5 1006.62   764.4 1012.69   784.3 1022.26   804.1 1028.77
   843.8  1038.5   933.2 1055.53  1012.6  1072.8  1052.3 1082.92  1092.1  1095.2
#Mann= 3 , 0 , 0
       0      .1       0     546    .045       0   553.5      .1       0
Bank Sta=546,553.5
XS Rating Curve= 0 ,0
Exp/Cntr=0.3,0.1

Type RM Length L Ch R = 1 ,1175.8  ,143.5,145.4,147.2
XS GIS Cut Line= 2
     1917296.248      420263.675     1917215.955      420683.273
#Sta/Elev= 30
       0  971.44    19.9  959.95    59.6  935.24    79.5  921.95   129.2  887.74
   139.1  880.39     149  872.29   168.9  854.87   178.8  845.37   188.8  836.52
   198.7  831.99   204.7  832.51   208.6  832.85   218.6  838.76   228.5  847.98
   238.4  856.61   248.4  863.87   268.2  879.54   288.1  896.18     308  913.62
   317.9  921.04   327.9  927.37   357.7  948.47   367.6  956.36   377.5  966.12
   387.5  974.72   397.4   979.5   407.3  981.26   417.3  981.86   427.2  981.95
#Mann= 3 , 0 , 0
       0      .1       0   198.7    .045       0   204.7      .1       0
Bank Sta=198.7,204.7
XS Rating Curve= 0 ,0
Exp/Cntr=0.3,0.1

Type RM Length L Ch R = 1 ,1030.4  ,294,300.4,305
XS GIS Cut Line= 3
     1917327.195       419910.14     1917136.956      420358.214
     1916971.658      420951.235
#Sta/Elev= 30
       0 1093.02    59.6 1080.54    79.5 1074.32   139.1 1046.61   248.4  998.77
     298  974.65   327.8     958   367.6  933.36   486.8   851.4   526.5     826
   536.4  819.07   546.4  807.21   556.3  797.28     566   795.2   576.2   803.3
     596  830.53   635.7   870.7   665.5  902.92     735   969.5     745  976.76
   754.9  981.42   844.2 1012.08   893.9 1030.91   913.8 1035.73   943.5 1038.85
   953.5  1041.3   963.4 1046.01    1013 1075.94  1062.7 1104.14  1102.4 1125.05
#Mann= 3 , 0 , 0
       0      .1       0   556.3    .045       0     566      .1       0
Bank Sta=556.3,566
XS Rating Curve= 0 ,0
Exp/Cntr=0.3,0.1

Type RM Length L Ch R = 1 ,729.9   ,717.1,729.5,743.5
XS GIS Cut Line= 3
     1917159.817       419800.23     1916875.071      420260.344
     1916611.426      420768.344
#Sta/Elev= 30
       0  883.88     9.8   879.7    19.7  882.25    29.5  891.54    39.4   907.7
    49.2  915.18      59   914.6   127.9  883.81   196.8  884.76     305  850.54
     364  837.77   383.7  827.34   413.2  803.35   491.9  730.98   521.4   697.9
   533.6   692.9   541.1  692.65   548.6  694.68   600.3  723.31   669.4  782.28
   689.1  802.52   708.8  829.19   758.2  905.41   768.1   923.4   787.8  971.42
   797.7  988.98   807.5  993.97   886.5  1008.2  1024.6 1039.98  1113.4  1053.6
#Mann= 3 , 0 , 0
       0      .1       0   533.6    .045       0   548.6      .1       0
Bank Sta=533.6,548.6
XS Rating Curve= 0 ,0
Exp/Cntr=0.3,0.1

Chan Stop Cuts=-1
Use User Specified Reach Order=0
Composite Channel Slope=5